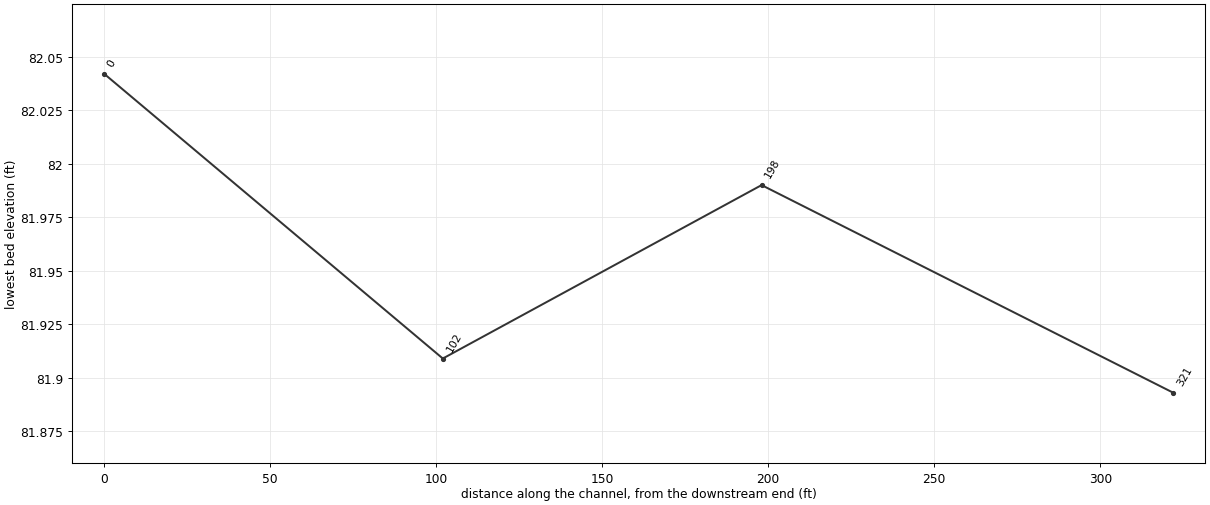
--- white-river.prj (project) ---

Proj Title=white-river
Current Plan=p01
Default Exp/Contr=0.3,0.1
English Units
Geom File=g01
Flow File=f01
Plan File=p01
Y Axis Title=Elevation
X Axis Title(PF)=Main Channel Distance
X Axis Title(XS)=Station
BEGIN DESCRIPTION:
END DESCRIPTION:
DSS Export Rating Curves= 0
DSS Export Rating Curve Sorted= 0
DSS Export Volume Flow Curves= 0
DXF OffsetX= 0
DXF OffsetY= 0
DXF ScaleX= 1
DXF ScaleY= 10

--- white-river.p01 (plan) ---

Plan Title=Plan 01
Program Version=4.10
Short Identifier=Plan 01
Geom File=g01
Flow File=f01
Subcritical Flow
K Sum by GR= 0
Std Step Tol= 0.01
Critical Tol= 0.01
Num of Std Step Trials= 20
Max Error Tol= 0.3
Flow Tol Ratio= 0.001
Split Flow NTrial= 30
Split Flow Tol= 0.02
Split Flow Ratio= 0.02
Log Output Level= 0
Friction Slope Method= 1
Unsteady Friction Slope Method= 2
Unsteady Bridges Friction Slope Method= 1
Parabolic Critical Depth
Global Vel Dist= 0 , 0 , 0
Global Log Level= 0
CheckData=True
Encroach Param=-1 ,0,0, 0
Computation Interval=1HOUR
Output Interval=1HOUR
Run HTab= 0
Run UNet= 0
Run PostProcess= 0
Run WQNet= 0
UNET Theta= 1
UNET Theta Warmup= 1
UNET ZTol= 0.02
UNET ZSATol= 0.05
UNET MxIter= 20
UNET MaxInSteps= 0
UNET DtIC= 0
UNET DtMin= 0
UNET MaxCRTS= 20
UNET WFStab= 2
UNET SFStab= 1
UNET WFX= 1
UNET SFX= 1
UNET DSS MLevel= 4
UNET DZMax Abort= 100
UNET Convert EG Bridges= 0
UNET Use Existing IB Tables=-1
UNET Froude Reduction=False
UNET Froude Limit= 1
UNET Froude Power= 10
UNET Time Slicing=0,0, 5
UNET Junction Losses=0
Instantaneous Interval=1HOUR
Write IC File= 0
Write IC File at Sim End=0
Echo Input=False
Echo Parameters=False
Echo Output=False
Write Detailed= 0
WQ AD Non Conservative
WQ ULTIMATE=-1
WQ Max Comp Step=1HOUR
WQ Output Interval=15MIN
WQ Output Selected Increments= 0
WQ Output face flow=0
WQ Output face velocity=0
WQ Output face area=0
WQ Output face dispersion=0
WQ Output cell volume=0
WQ Output cell surface area=0
WQ Output cell continuity=0
WQ Output cumulative cell continuity=0
WQ Output face conc=0
WQ Output face dconc_dx=0
WQ Output face courant=0
WQ Output face peclet=0
WQ Output face adv mass=0
WQ Output face disp mass=0
WQ Output cell mass=0
WQ Output cell source sink temp=0
WQ Output cell source sink nsm=0
WQ Output MaxMinRange=-1
WQ Daily Max Min Mean=-1
WQ Daily Range=0
WQ Daily Time=0
WQ Create Restart=0
WQ Fixed Restart=0
WQ System Summary=0
WQ Use Fixed Temperature=0
Sorting and Armoring Iterations= 10
XS Update Threshold= 0.02
Hydraulics Update Threshold= 0.02
Energy Slope Method= 1
Volume Change Method= 0
XS Weighting Method= 0
Number of US Weighted Cross Sections= 1
Number of DS Weighted Cross Sections= 1
Upstream XS Weight=0.25
Main XS Weight=0.5
Downstream XS Weight=0.25
Number of DS XS's Weighted with US Boundary= 1
Upstream Boundary Weight= 1
Weight of XSs Associated with US Boundary= 0
Number of US XS's Weighted with DS Boundary= 1
Downstream Boundary Weight= 0.5
Weight of XSs Associated with DS Boundary= 0.5
Sediment Output Level= 4
Mass or Volume Output= 0
Output Increment Type= 1
Profile and TS Output Increment= 10
XS Output Flag= 0
XS Output Increment= 10
Disregard all LS=0
Disregard all Conn=0
Disregard all Breaches=0
Disregard all Pumps=0

--- white-river.f01 (steady flow) ---

Flow Title=white-river-ss
Program Version=4.10
Number of Profiles= 1
Profile Names=PF 1
River Rch & RM=WhiteRiver,SilverFalls     ,321
    1900
Boundary for River Rch & Prof#=WhiteRiver,SilverFalls     , 1
Up Type= 2
Dn Type= 2
DSS Import GetInterval= 0
DSS Import GetPeak= 0
DSS Import FillOption= 0

--- white-river.g01 (geometry) ---

Geom Title=white-river
Program Version=4.10

River Reach=WhiteRiver      ,SilverFalls
Reach XY= 3
0.013833992094860.901185770750990.333992094861660.10079051383399
0.333992094861660.10079051383399

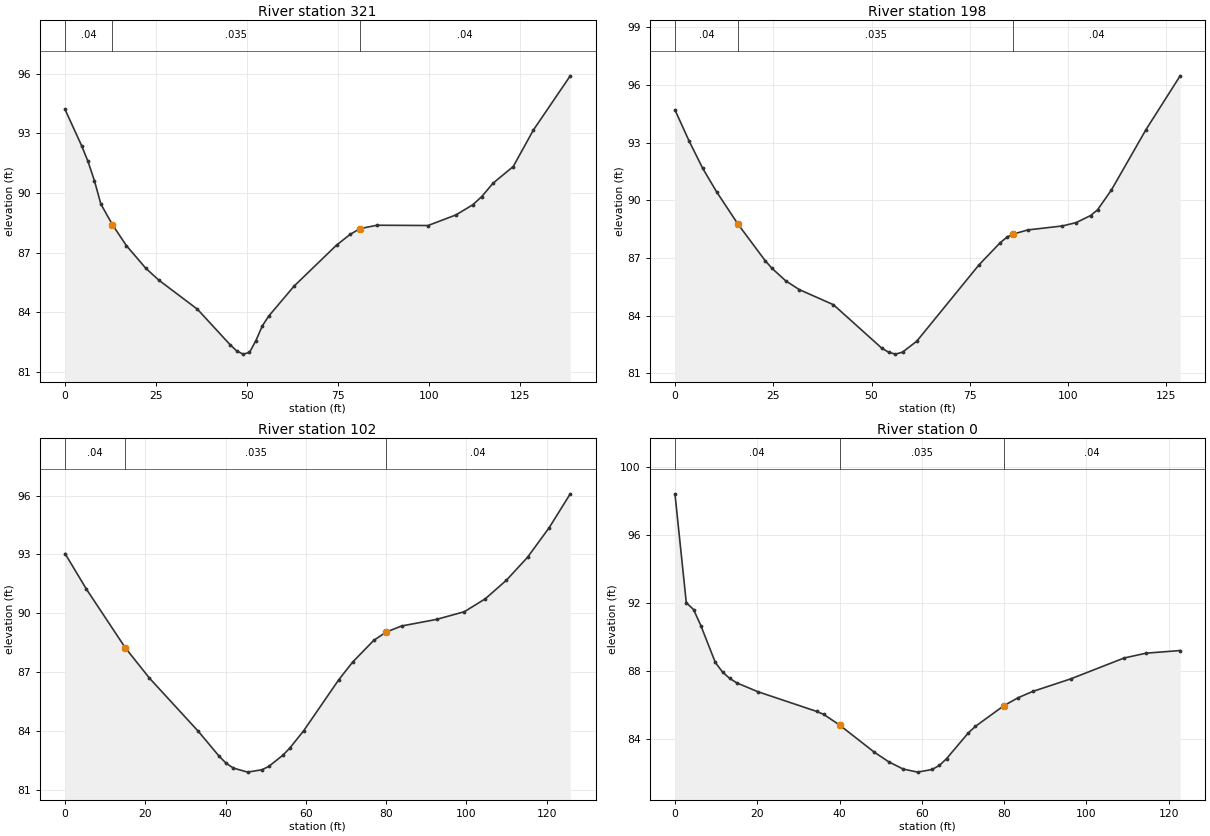
Type RM Length L Ch R = 1 ,321     ,124,124,124
#Sta/Elev= 30
       0  94.196   4.534  92.381   6.302  91.582   8.071  90.611   9.838  89.439
      13  88.406  16.833  87.353  22.206  86.205   25.79  85.609  36.369   84.15
   45.35  82.363  47.119   82.06  48.887  81.893  50.656  81.976  52.424  82.575
  54.193  83.318  55.962  83.811  62.899  85.312  74.575  87.376  78.323  87.916
      81  88.204  85.696  88.375  99.701   88.36 107.322   88.89 112.027  89.407
 114.452  89.818 117.596  90.496 123.097  91.326 128.597  93.151 138.758  95.887
#Mann= 3 , 0 , 0
       0     .04       0      13    .035       0      81     .04       0
Bank Sta=13,81
XS Rating Curve= 0 ,0
Exp/Cntr=0.3,0.1

Type RM Length L Ch R = 1 ,198     ,96,96,96
BEGIN DESCRIPTION:
Station-2
END DESCRIPTION:
#Sta/Elev= 27
       0  94.701   3.591  93.084   7.071  91.654  10.618  90.429      16  88.764
  22.923  86.861  24.663  86.459  28.143   85.81  31.623  85.348  40.324  84.561
  52.583  82.306  54.335   82.09  56.092   81.99  57.902  82.094  61.521  82.665
  77.313  86.629   82.74   87.79  84.504  88.083      86  88.235  89.746  88.452
  98.549   88.66 102.058  88.834  105.74  89.203 107.503  89.502 111.019  90.529
  119.83  93.677 128.512  96.472
#Mann= 3 , 0 , 0
       0     .04       0      16    .035       0      86     .04       0
Bank Sta=16,86
XS Rating Curve= 0 ,0
Exp/Cntr=0.3,0.1

Type RM Length L Ch R = 1 ,102     ,102,102,102
BEGIN DESCRIPTION:
Station-3
END DESCRIPTION:
#Sta/Elev= 26
       0  93.046   5.331  91.231      15  88.249  21.025  86.699  33.206  83.987
  38.426  82.711  40.169  82.355  41.943  82.114  45.492  81.909  49.039  82.029
  50.779  82.204  54.259  82.769  55.999  83.136   59.48  84.026   68.18  86.614
   71.66  87.518   76.88  88.618      80  89.045  83.841  89.356  92.541  89.691
  99.502  90.085 104.722  90.746 109.942  91.685 115.225  92.857  120.62  94.368
 125.863   96.09
#Mann= 3 , 0 , 0
       0     .04       0      15    .035       0      80     .04       0
Bank Sta=15,80
XS Rating Curve= 0 ,0
Exp/Cntr=0.3,0.1

Type RM Length L Ch R = 1 ,0       ,1,1,1
BEGIN DESCRIPTION:
DownstreamStation
END DESCRIPTION:
#Sta/Elev= 28
       0    98.4   2.757      92   4.521  91.599   6.285   90.66   9.814  88.488
  11.568  87.924  13.316  87.551  15.063  87.284  20.186  86.766  34.417  85.613
  36.185  85.433      40  84.813  48.473  83.212   51.96  82.651  55.454  82.225
  58.982  82.042   62.51  82.197  64.274  82.436  66.025  82.834  71.245  84.329
  72.991  84.724      80  85.955  83.459   86.42  86.939  86.782  96.185  87.521
 109.194  88.751 114.522  89.034 122.811  89.189
#Mann= 3 , 0 , 0
       0     .04       0      40    .035       0      80     .04       0
Bank Sta=40,80
XS Rating Curve= 0 ,0
Exp/Cntr=0.3,0.1

Chan Stop Cuts=-1
Use User Specified Reach Order=0
Composite Channel Slope=5